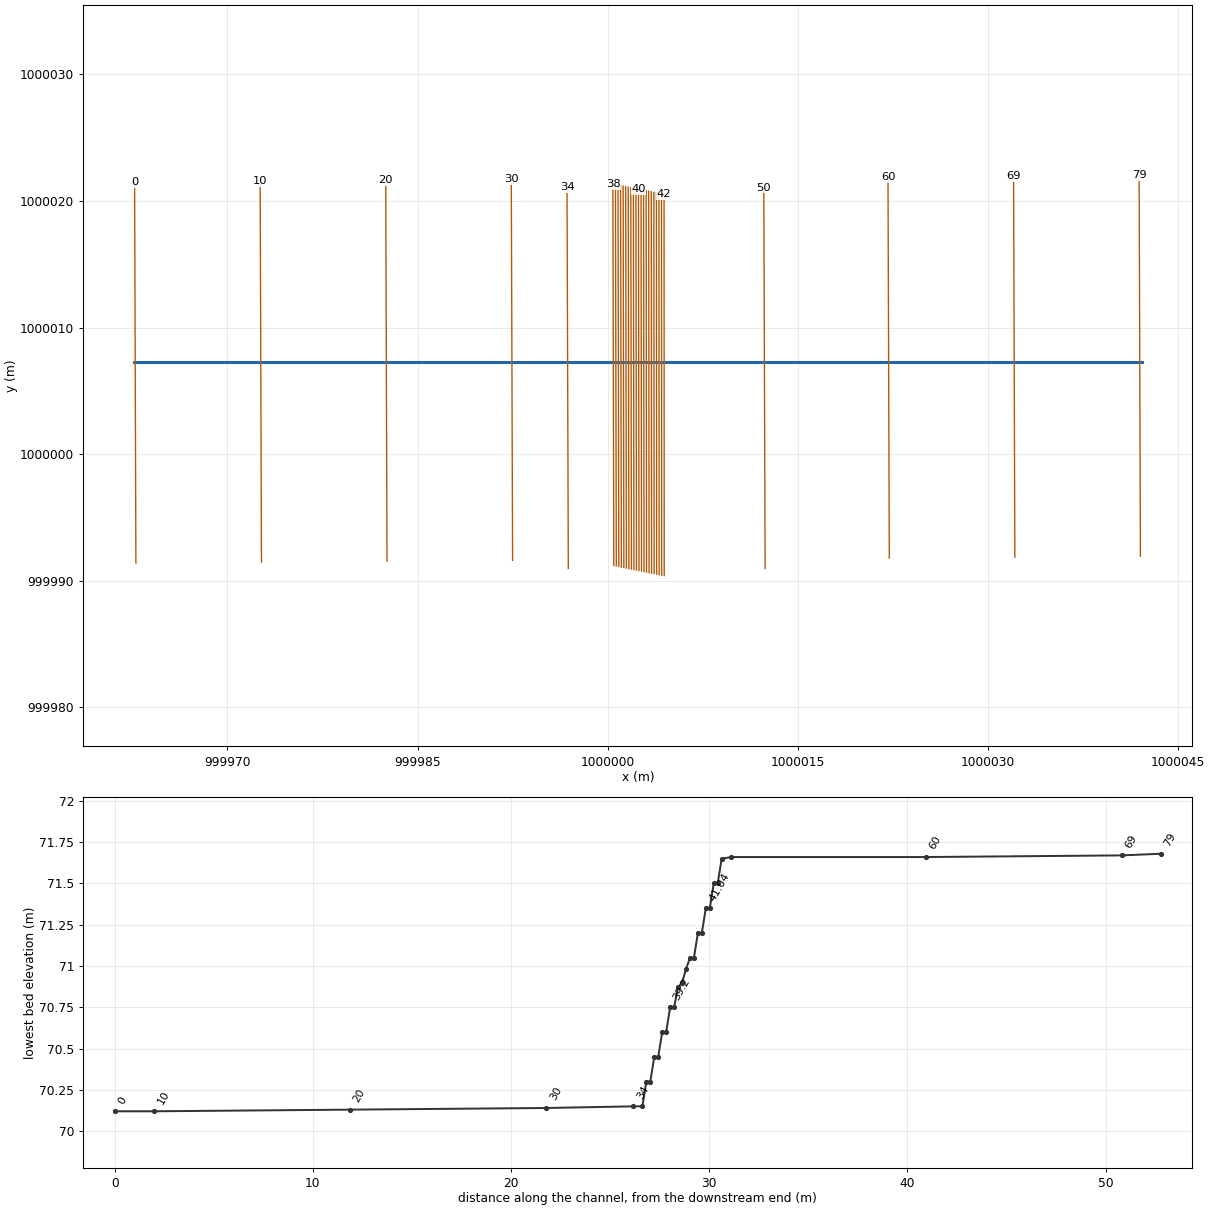
--- EECL2.prj (project) ---

Proj Title=EstructuraEscalonada2
Current Plan=p01
Default Exp/Contr=0.3,0.1
SI Units
Geom File=g01
Flow File=f01
Flow File=f02
Flow File=f03
Unsteady File=u01
Plan File=p02
Plan File=p03
Plan File=p01
Y Axis Title=Elevation
X Axis Title(PF)=Main Channel Distance
X Axis Title(XS)=Station
BEGIN DESCRIPTION:
END DESCRIPTION:
DSS File=dss
DSS Export Rating Curves= 0
DSS Export Rating Curve Sorted= 0
DSS Export Volume Flow Curves= 0
DXF OffsetX= 0
DXF OffsetY= 0
DXF ScaleX= 1
DXF ScaleY= 10

--- EECL2.p01 (plan) ---

Plan Title=UnsteadyLibre
Program Version=6.70
Short Identifier=UnsteadyLibre
Simulation Date=01SEP2008,0015,02SEP2008,0015
Geom File=g01
Flow File=u01
Subcritical Flow
K Sum by GR= 0
Std Step Tol= 0.003
Critical Tol= 0.003
Num of Std Step Trials= 20
Max Error Tol= 0.1
Flow Tol Ratio= 0.001
Split Flow NTrial= 30
Split Flow Tol= 0.006
Split Flow Ratio= 0.02
Log Output Level= 0
Friction Slope Method= 1
Unsteady Friction Slope Method= 2
Unsteady Bridges Friction Slope Method= 1
Calc Critical at every XS
Parabolic Critical Depth
Global Vel Dist= 0 , 0 , 0
Global Log Level= 0
CheckData=False
Encroach Param=-1 ,0,0, 0
Flow Ratio Tolerance=0.1
Flow Ratio Min Ratio=0.5
Flow Ratio Max Ratio=4
Flow Ratio Max Iterations= 10
Computation Interval=1MIN
Output Interval=15MIN
Instantaneous Interval=15MIN
Mapping Interval=15MIN
Computation Time Step Use Courant=        0
Computation Time Step Use Time Series=    0
Computation Time Step Count To Double=0
Computation Time Step Max Doubling=0
Computation Time Step Max Halving=0
Computation Time Step Residence Courant=0
Run HTab=-1
Run UNet=-1
Run Sediment= 0
Run PostProcess=-1
Run WQNet= 0
Run RASMapper= 0
UNET Theta= 1
UNET Theta Warmup= 1
UNET ZTol= 0.006
UNET ZSATol= 0.006
UNET MxIter= 20
UNET Max Iter WO Improvement= 0
UNET MaxInSteps= 0
UNET DtIC= 0
UNET DtMin= 0
UNET MaxCRTS= 20
UNET WFStab= 2
UNET SFStab= 1
UNET WFX= 1
UNET SFX= 1
UNET Gravity=9.80665
UNET 1D Methodology=Finite Difference
UNET DSS MLevel= 4
UNET Pardiso=0
UNET DZMax Abort= 30
UNET Use Existing IB Tables=-1
UNET Froude Reduction=False
UNET Froude Limit= 0.8
UNET Froude Power= 4
UNET D1 Cores= 0
UNET WindReference=Eulerian
UNET WindDragFormulation=Hsu (1988)
UNET D2 Coriolis=0
UNET D2 Cores= 0
UNET D2 Theta= 1
UNET D2 Theta Warmup= 1
UNET D2 Z Tol= 0.003
UNET D2 Volume Tol= 0.003
UNET D2 Max Iterations= 20
UNET D2 Advanced Convergence=0
UNET D2 WS Max Tol=0.045
UNET D2 WS RMS Tol=0.006
UNET D2 WS Stall Tol=1
UNET D2 Equation= 0
UNET D2 RampUpFraction=0.1
UNET D2 TimeSlices= 1
UNET D2 Turbulence Formulation=None
UNET D2 Eddy Viscosity=0.3
UNET D2 Transverse Eddy Viscosity=0.1
UNET D2 Smagorinsky Mixing=0.05
UNET D2 BCVolumeCheck=0
UNET D2 Cores=0
UNET D2 SolverType=PARDISO (Direct)
UNET D2 Minimum Iterations= 3
UNET D2 Maximum Iterations= 30
UNET D2 Restart Number= 10
UNET D2 Relaxation Coeff=1.3
UNET D2 SOR Precondition Iterations= 10
UNET D2 ILUT Maximum Fill= 8
UNET D2 ILUT Tolerance=1E-08
UNET D2 Convergence Tolerance=0.00001
Secondary Flow Approach=None
Spiral Intensity Factor=1
Spiral Intensity Adaptation Factor=1
Spiral Intensity Diffusion Factor=1
Momentum Dispersion Factor=1
Flow Smoothing Iterations=10
PS Theta= 1
PS WS Tol= 0.003
PS Volume Tol= 0.003
PS Max Iterations= 20
PS Equation= 0
PS Advance Time Step=-1
PS Target Courant=0.9
PS Time Slices= 1
PS Iterate With 2D=0
PS Project Initial WSE from DS=-1
PS Ramp Up Initial WSE from US=-1
PS Cores=0
UNET D1D2 MaxIter= 0
UNET D1D2 ZTol=0.003
UNET D1D2 QTol=0.1
UNET D1D2 MinQTol=0.03
DSS File=dss
Write IC File= 0
Write IC File at Fixed DateTime=0
Write IC File at Sim End=0
Echo Input=False
Echo Parameters=False
Echo Output=False
Write Detailed= 0
HDF Write Warmup=0
HDF Write Time Slices=0
HDF Flush=0
HDF Compression= 1
HDF Chunk Size= 1
HDF Spatial Parts= 1
HDF Use Max Rows=0
HDF Fixed Rows= 1
Calibration Method= 0
Calibration Iterations= 20
Calibration Max Change=0.05
Calibration Tolerance=0.2
Calibration Maximum=1.5
Calibration Minimum=0.5
Calibration Optimization Method= 1
WQ AD Non Conservative
WQ ULTIMATE=-1
WQ Max Comp Step=1HOUR
WQ Output Interval=15MIN
WQ Output Selected Increments= 0
WQ Create Restart=0
WQ Fixed Restart=0
WQ System Summary=0
WQ Write To DSS=0
Sorting and Armoring Iterations= 10
XS Update Threshold= 0.02
Bed Roughness Predictor= 0
Processes Affected by Predictor=Sediment Only
Hydraulics Update Threshold= 0.02
Energy Slope Method= 1
Volume Change Method= 1
Sediment Retention Method= 0
Sediment TS Multiplier= 1
Warm Up Method= 0
XS Weighting Method= 0
Number of US Weighted Cross Sections= 1
Number of DS Weighted Cross Sections= 1
Upstream XS Weight=0
Main XS Weight=1
Downstream XS Weight=0
Number of DS XS's Weighted with US Boundary= 1
Upstream Boundary Weight= 1
Weight of XSs Associated with US Boundary= 0
Number of US XS's Weighted with DS Boundary= 1
Downstream Boundary Weight= 0.5
Weight of XSs Associated with DS Boundary= 0.5
Percentile Method= 0
Sediment Output Level= 3
Mass or Volume Output= 0
Output Increment Type= 1
Profile and TS Output Increment= 1
Transport Output Increment 1
XS Output Flag= 0
XS Output Increment= 10
Read HDF5 Sediment Hotstart= 0
Sediment Hotstart Type= 0
Write Gradation File= 0
Read Gradation Hotstart= 0
Write HDF5 File= 1
Write Binary Output= 1
Write DSS Sediment File= 0
DSS Sediment Output Type= 1
SV Curve= 0
Specific Gage Flag= 0
Subcell Erosion Methods= 0
Subcell Deposition Methods= 0
Advection Scheme= 1
Matrix Solver= 0
Implicit Weighting Factor= 1
Maximum Outer Loop Convergence Iterations= 5
Convergence Maximum Absolute= 0.001
Convergence RMSE= 0.0001
Grain Fractions Max Abs Error= 0.001
Max Subgrid Regions= 1
Max Subgrid Length Scale= 3.402823E+38
Initial Layer Thickness= 3
Min Layer Thickness= 0.1
Max Layer Thickness= 6
Number of Layers= 5

--- EECL2.p02 (plan) ---

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Plan Title=SteadyLibre
Short Identifier=SteadyLibre
Geom File=g01
Flow File=f02
CheckData=True
Output Interval=1HOUR
Instantaneous Interval=1HOUR
Mapping Interval=1HOUR
Run HTab= 0
Run UNet= 0
Run PostProcess= 0

--- EECL2.p03 (plan) ---

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Plan Title=SteadyLaminaDominante
Short Identifier=SteadyLaminaDominante
Geom File=g01
Flow File=f03
Output Interval=1HOUR
Instantaneous Interval=1HOUR
Mapping Interval=1HOUR
Run HTab= 0
Run UNet= 0
Run PostProcess= 0

--- EECL2.f01 (steady flow) ---

Flow Title=Steady
Program Version=6.70
Number of Profiles= 6
Profile Names=TR2.33yr,TR5yr,TR10yr,TR25yr,TR50yr,TR100yr
River Rch & RM=CauceLateral,CauceLateral    ,79
      42    59.5    74.2    93.3   107.7   122.2
Boundary for River Rch & Prof#=CauceLateral,CauceLateral    , 1
Up Type= 0
Dn Type= 3
Dn Slope=0.000932
Boundary for River Rch & Prof#=CauceLateral,CauceLateral    , 2
Up Type= 0
Dn Type= 3
Dn Slope=0.000932
Boundary for River Rch & Prof#=CauceLateral,CauceLateral    , 3
Up Type= 0
Dn Type= 3
Dn Slope=0.000932
Boundary for River Rch & Prof#=CauceLateral,CauceLateral    , 4
Up Type= 0
Dn Type= 3
Dn Slope=0.000932
Boundary for River Rch & Prof#=CauceLateral,CauceLateral    , 5
Up Type= 0
Dn Type= 3
Dn Slope=0.000932
Boundary for River Rch & Prof#=CauceLateral,CauceLateral    , 6
Up Type= 0
Dn Type= 3
Dn Slope=0.000932
DSS Import GetInterval= 0
DSS Import GetPeak= 0
DSS Import FillOption= 0

--- EECL2.f02 (steady flow) ---

Flow Title=SteadyLibre
Program Version=6.70
Number of Profiles= 7
Profile Names=TR2.33yr,TR5yr,TR10yr,TR25yr,TR50yr,TR100yr,Qm
River Rch & RM=CauceLateral,CauceLateral    ,79
      42    59.5    74.2    93.3   107.7   122.2     .11
Boundary for River Rch & Prof#=CauceLateral,CauceLateral    , 1
Up Type= 0
Dn Type= 3
Dn Slope=0.000932
DSS Import GetInterval= 0
DSS Import GetPeak= 0
DSS Import FillOption= 0

--- EECL2.f03 (steady flow) ---

Flow Title=SteadyLaminaDominante
Program Version=6.70
Number of Profiles= 7
Profile Names=TR2.33yr,TR5yr,TR10yr,TR25yr,TR50yr,TR100yr,Qm
River Rch & RM=CauceLateral,CauceLateral    ,79
      42    59.5    74.2    93.3   107.7   122.2     .11
Boundary for River Rch & Prof#=CauceLateral,CauceLateral    , 1
Up Type= 0
Dn Type= 1
Dn Known WS=1.5
DSS Import GetInterval= 0
DSS Import GetPeak= 0
DSS Import FillOption= 0

--- EECL2.u01 (unsteady flow) ---

Flow Title=UnsteadyLibre
Program Version=6.70
Use Restart= 0
Initial Flow Loc=CauceLateral    ,CauceLateral    ,79      ,1
Boundary Location=CauceLateral    ,CauceLateral    ,79      ,        ,                ,                ,                ,                                ,                                ,
Interval=1MIN
Flow Hydrograph= 4321
       0       0       0       0       0       0       0       0       0       0
       0       0       0       0       0       0       0       0       0       0
       0      .1      .1      .1      .1      .1      .1      .1      .2      .2
      .2      .2      .3      .3      .3      .4      .4      .5      .5      .5
      .6      .6      .7      .8      .8      .9       1       1     1.1     1.2
     1.3     1.4     1.4     1.5     1.6     1.7     1.8       2     2.1     2.2
     2.3     2.4     2.6     2.7     2.8       3     3.1     3.3     3.4     3.6
     3.7     3.9     4.1     4.2     4.4     4.6     4.8       5     5.2     5.4
     5.6     5.8       6     6.2     6.4     6.7     6.9     7.1     7.4     7.6
     7.9     8.2     8.4     8.7       9     9.2     9.5     9.8    10.1    10.4
    10.7      11    11.4    11.7      12    12.4    12.7    13.1    13.4    13.8
    14.2    14.5    14.9    15.3    15.7    16.1    16.5    16.9    17.4    17.8
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Stage Hydrograph TW Check=0
Use DSS=False
Use Fixed Start Time=False
Is Critical Boundary=False
Boundary Location=CauceLateral    ,CauceLateral    ,0       ,        ,                ,                ,                ,                                ,                                ,
Friction Slope=0.000932
Precipitation Mode=Disable
Wind Mode=No Wind Forces
Wave Mode=No Wave Forcing
Met BC=Precipitation|Expanded View=0
Met BC=Precipitation|Point Interpolation=Nearest
Met BC=Precipitation|Gridded Source=DSS
Met BC=Precipitation|Gridded Interpolation=
Met BC=Evapotranspiration|Expanded View=0
Met BC=Evapotranspiration|Point Interpolation=Nearest
Met BC=Evapotranspiration|Gridded Source=DSS
Met BC=Evapotranspiration|Gridded Interpolation=
Met BC=Wind Speed|Expanded View=0
Met BC=Wind Speed|Point Interpolation=Nearest
Met BC=Wind Speed|Gridded Source=DSS
Met BC=Wind Speed|Gridded Interpolation=
Met BC=Wind Direction|Expanded View=0
Met BC=Wind Direction|Point Interpolation=Nearest
Met BC=Wind Direction|Gridded Source=DSS
Met BC=Wind Direction|Gridded Interpolation=
Met BC=Wind Velocity X|Expanded View=0
Met BC=Wind Velocity X|Point Interpolation=Nearest
Met BC=Wind Velocity X|Gridded Source=DSS
Met BC=Wind Velocity X|Gridded Interpolation=
Met BC=Wind Velocity Y|Expanded View=0
Met BC=Wind Velocity Y|Point Interpolation=Nearest
Met BC=Wind Velocity Y|Gridded Source=DSS
Met BC=Wind Velocity Y|Gridded Interpolation=
Met BC=Wave Forcing X|Expanded View=0
Met BC=Wave Forcing X|Point Interpolation=Nearest
Met BC=Wave Forcing X|Gridded Source=DSS
Met BC=Wave Forcing X|Gridded Interpolation=
Met BC=Wave Forcing Y|Expanded View=0
Met BC=Wave Forcing Y|Point Interpolation=Nearest
Met BC=Wave Forcing Y|Gridded Source=DSS
Met BC=Wave Forcing Y|Gridded Interpolation=
Met BC=Air Density|Mode=Constant
Met BC=Air Density|Expanded View=0
Met BC=Air Density|Constant Value=1.225
Met BC=Air Density|Constant Units=kg/m3
Met BC=Air Density|Point Interpolation=Nearest
Met BC=Air Density|Gridded Source=DSS
Met BC=Air Density|Gridded Interpolation=
Met BC=Air Temperature|Expanded View=0
Met BC=Air Temperature|Point Interpolation=Nearest
Met BC=Air Temperature|Gridded Source=DSS
Met BC=Air Temperature|Gridded Interpolation=
Met BC=Humidity|Expanded View=0
Met BC=Humidity|Point Interpolation=Nearest
Met BC=Humidity|Gridded Source=DSS
Met BC=Humidity|Gridded Interpolation=
Met BC=Air Pressure|Mode=Constant
Met BC=Air Pressure|Expanded View=0
Met BC=Air Pressure|Constant Value=1013.2
Met BC=Air Pressure|Constant Units=mb
Met BC=Air Pressure|Point Interpolation=
Met BC=Air Pressure|Gridded Source=DSS
Met BC=Air Pressure|Gridded Interpolation=
Non-Newtonian Method= 0 ,
Non-Newtonian Constant Vol Conc=0
Non-Newtonian Yield Method= 0 ,
Non-Newtonian Yield Coef=0, 0
User Yeild=   0
Non-Newtonian Sed Visc= 0 ,
Non-Newtonian Obrian B=0
User Viscosity=0
User Viscosity Ratio=0
Herschel-Bulkley Coef=0, 0
Clastic Method= 0 ,
Coulomb Phi=0
Voellmy X=0
Non-Newtonian Hindered FV= 0
Non-Newtonian FV K=0
Non-Newtonian ds=0
Non-Newtonian Max Cv=0
Non-Newtonian Bulking Method= 0 ,
Non-Newtonian High C Transport= 0 ,
Lava Activation= 0
Temperature=1300,15,,15,14,980
Heat Ballance=1,1200,0.5,1,70,0.95
Viscosity=1000,,,
Profile Coefficient=4,1.3,
Lava Param=,2500,

--- EECL2.g01 (geometry) ---

Geom Title=EscalonadaLateral2
Program Version=6.70

River Reach=CauceLateral    ,CauceLateral
Reach XY= 2
1000042.148480941000007.28109675999962.6134121591000007.28109675

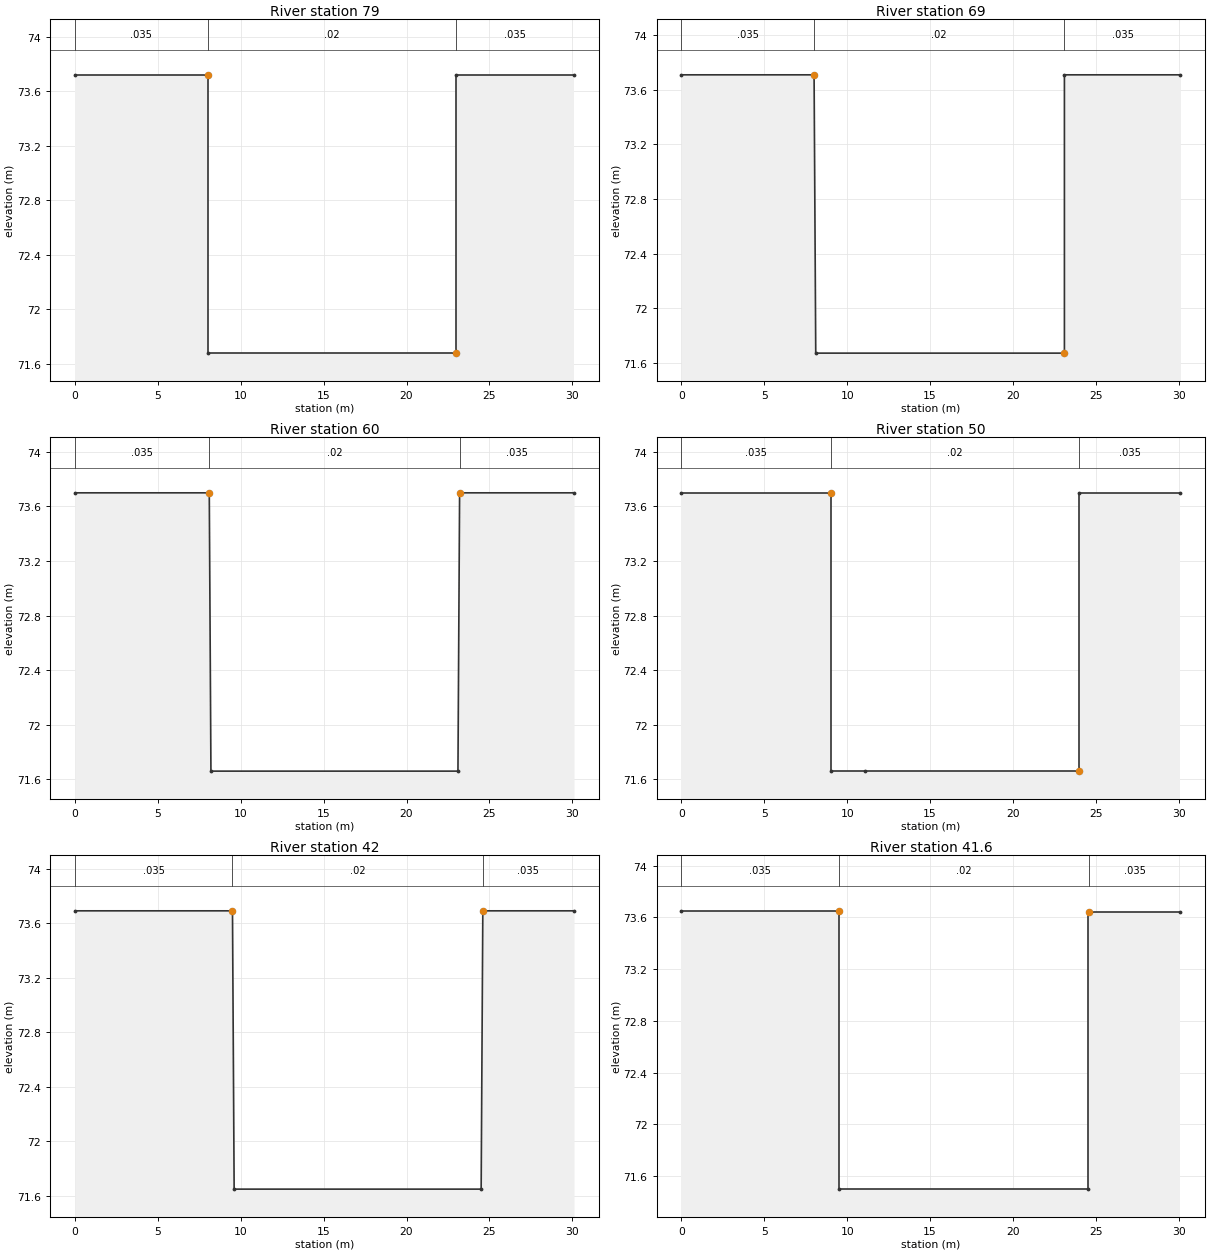
Type RM Length L Ch R = 1 ,79      ,1.98,1.98,1.98
XS GIS Cut Line= 2
1000042.02034848999991.9327833311000041.918814251000022.02075938
#Sta/Elev= 6
       0   73.72       8   73.72       8   71.68      23   71.68      23   73.72
    30.1   73.72
#Mann= 3 ,0,0
       0    .035       0       8     .02       0      23    .035       0
Bank Sta=8,23
XS Rating Curve= 0 ,0
Exp/Cntr(USF)=0,0
Exp/Cntr=0.3,0.1

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
Type RM Length L Ch R = 1 ,69      ,9.9,9.9,9.9
XS GIS Cut Line= 2
1000032.11599962999991.8672639341000032.014465391000021.95523998
#Sta/Elev= 6
       0   73.71       8   73.71     8.1   71.67    23.1   71.67    23.1   73.71
    30.1   73.71
#Mann= 3 ,0,0
       0    .035       0       8     .02       0    23.1    .035       0
Bank Sta=8,23.1
XS Rating Curve= 0 ,0
Exp/Cntr=0.3,0.1

Type RM Length L Ch R = 1 ,60      ,9.8,9.8,9.8
XS GIS Cut Line= 2
1000022.21165076999991.8017445371000022.110116541000021.88972059
#Sta/Elev= 6
       0    73.7     8.1    73.7     8.2   71.66    23.1   71.66    23.2    73.7
    30.1    73.7
#Mann= 3 ,0,0
       0    .035       0     8.1     .02       0    23.2    .035       0
Bank Sta=8.1,23.2
XS Rating Curve= 0 ,0
Exp/Cntr=0.3,0.1

Type RM Length L Ch R = 1 ,50      ,0.494,0.494,0.494
XS GIS Cut Line= 2
1000012.41644179999990.9634246881000012.314907561000021.05140074
#Sta/Elev= 7
       0    73.7       9    73.7       9   71.66    11.1   71.66      24   71.66
      24    73.7    30.1    73.7
#Mann= 3 ,0,0
       0    .035       0       9     .02       0      24    .035       0
Bank Sta=9,24
XS Rating Curve= 0 ,0
Exp/Cntr=0.3,0.1

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
Type RM Length L Ch R = 1 ,42      ,0.2,0.2,0.2
XS GIS Cut Line= 2
1000004.45826176999990.4032213081000004.446529121000020.50948505
#Sta/Elev= 6
       0   73.69     9.5   73.69     9.6   71.65    24.5   71.65    24.6   73.69
    30.1   73.69
#Mann= 3 ,0,0
       0    .035       0     9.5     .02       0    24.6    .035       0
Bank Sta=9.5,24.6
XS Rating Curve= 0 ,0
Exp/Cntr(USF)=0,0
Exp/Cntr=0.3,0.1

Type RM Length L Ch R = 1 ,41.6    ,0.2,0.2,0.2
XS GIS Cut Line= 2
 1000004.2593767999990.443169735 1000004.24473681000020.55048861
#Sta/Elev= 8
       0   73.65    9.46   73.65     9.5   73.65     9.5    71.5    24.5    71.5
    24.5   73.64   24.56   73.64    30.1   73.64
#Mann= 3 ,0,0
       0    .035       0     9.5     .02       0   24.56    .035       0
Bank Sta=9.5,24.56
XS Rating Curve= 0 ,0
Exp/Cntr=0.3,0.1

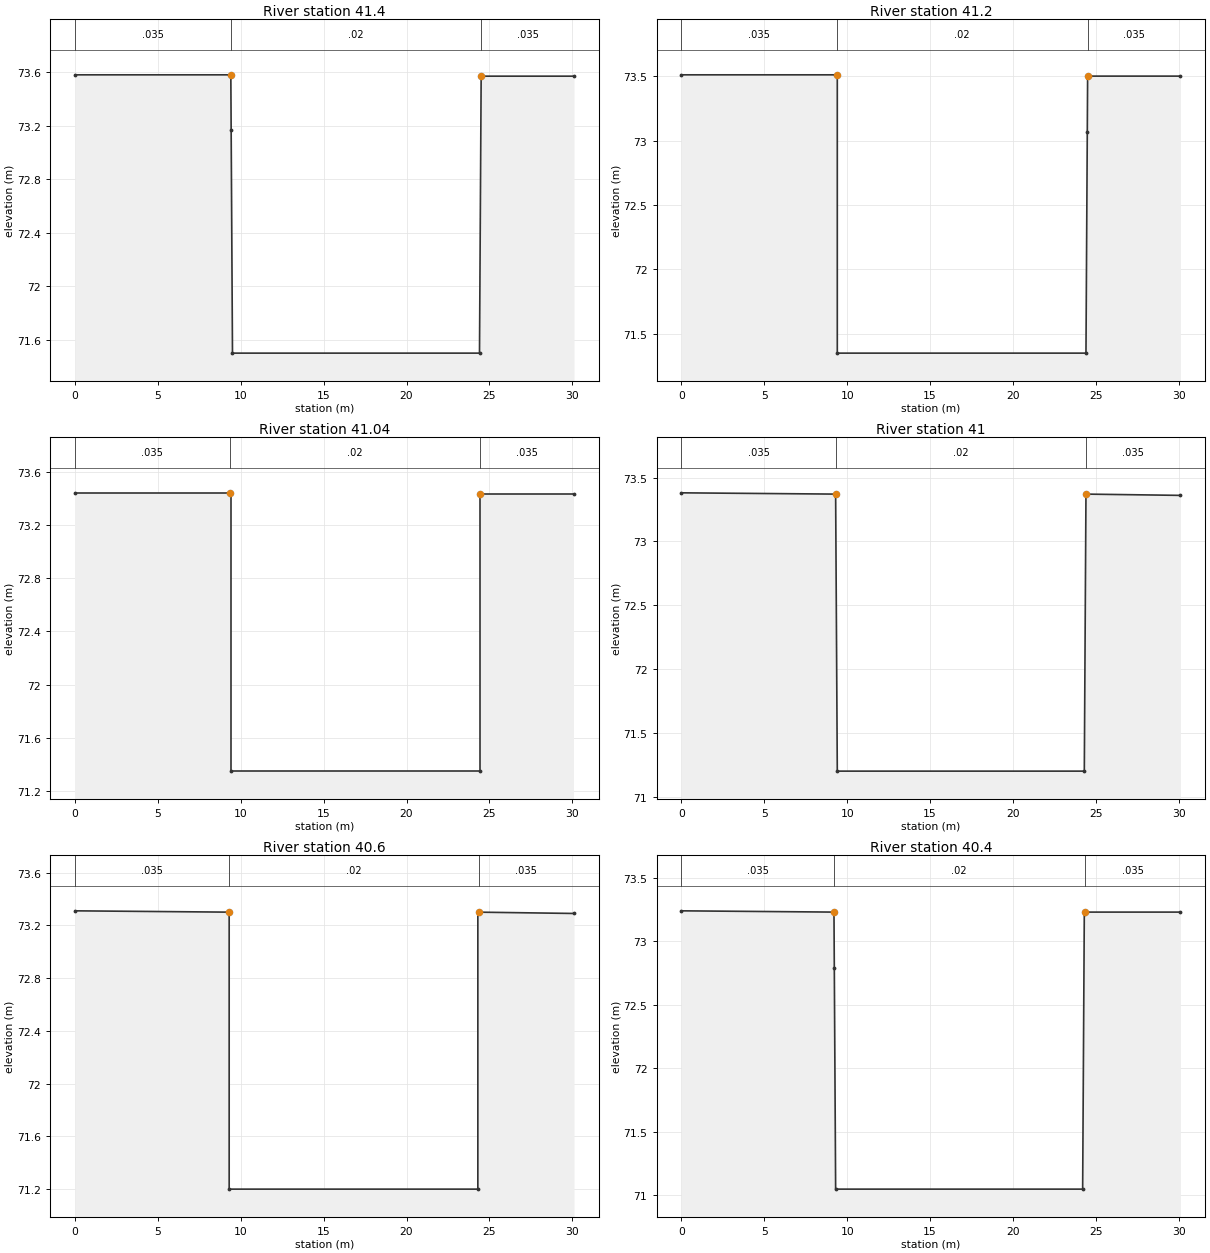
Type RM Length L Ch R = 1 ,41.4    ,0.2,0.2,0.2
XS GIS Cut Line= 2
1000004.06049164999990.4831181621000004.042944471000020.59149217
#Sta/Elev= 8
       0   73.58     9.4   73.58    9.4273.16399     9.5    71.5    24.4    71.5
    24.5   73.57   24.52   73.57    30.1   73.57
#Mann= 3 ,0,0
       0    .035       0     9.4     .02       0    24.5    .035       0
Bank Sta=9.4,24.5
XS Rating Curve= 0 ,0
Exp/Cntr=0.3,0.1

Type RM Length L Ch R = 1 ,41.2    ,0.2,0.2,0.2
XS GIS Cut Line= 2
1000003.86160657999990.5230665921000003.841152131000020.63249574
#Sta/Elev= 8
       0   73.51    9.38   73.51     9.4   73.51     9.4   71.35    24.4   71.35
   24.4873.06999    24.5    73.5    30.1    73.5
#Mann= 3 ,0,0
       0    .035       0    9.38     .02       0    24.5    .035       0
Bank Sta=9.38,24.5
XS Rating Curve= 0 ,0
Exp/Cntr=0.3,0.1

Type RM Length L Ch R = 1 ,41.04   ,0.2,0.2,0.2
XS GIS Cut Line= 2
1000003.66272152999990.5630150161000003.63935982 1000020.6734993
#Sta/Elev= 8
       0   73.44    9.34   73.44     9.4   73.44     9.4   71.35    24.4   71.35
    24.4   73.43   24.44   73.43    30.1   73.43
#Mann= 3 ,0,0
       0    .035       0    9.34     .02       0   24.44    .035       0
Bank Sta=9.34,24.44
XS Rating Curve= 0 ,0
Exp/Cntr=0.3,0.1

Type RM Length L Ch R = 1 ,41      ,0.2,0.2,0.2
XS GIS Cut Line= 2
1000003.46383648 999990.60296344 1000003.43756751000020.71450286
#Sta/Elev= 6
       0   73.38     9.3   73.37     9.4    71.2    24.3    71.2    24.4   73.37
    30.1   73.36
#Mann= 3 ,0,0
       0    .035       0     9.3     .02       0    24.4    .035       0
Bank Sta=9.3,24.4
XS Rating Curve= 0 ,0
Exp/Cntr=0.3,0.1

Type RM Length L Ch R = 1 ,40.6    ,0.2,0.2,0.2
XS GIS Cut Line= 2
1000003.26495138999990.6429118761000003.235775131000020.75550643
#Sta/Elev= 8
       0   73.31    9.2673.30005     9.3    73.3     9.3    71.2    24.3    71.2
    24.3    73.3   24.36 73.2999    30.1   73.29
#Mann= 3 ,0,0
       0    .035       0    9.26     .02       0   24.36    .035       0
Bank Sta=9.26,24.36
XS Rating Curve= 0 ,0
Exp/Cntr=0.3,0.1

Type RM Length L Ch R = 1 ,40.4    ,0.2,0.2,0.2
XS GIS Cut Line= 2
1000003.06606628999990.6828603121000003.03398276   1000020.79651
#Sta/Elev= 8
       0   73.24     9.2   73.23    9.22  72.794     9.3   71.05    24.2   71.05
    24.3   73.23   24.32   73.23    30.1   73.23
#Mann= 3 ,0,0
       0    .035       0     9.2     .02       0   24.32    .035       0
Bank Sta=9.2,24.32
XS Rating Curve= 0 ,0
Exp/Cntr=0.3,0.1

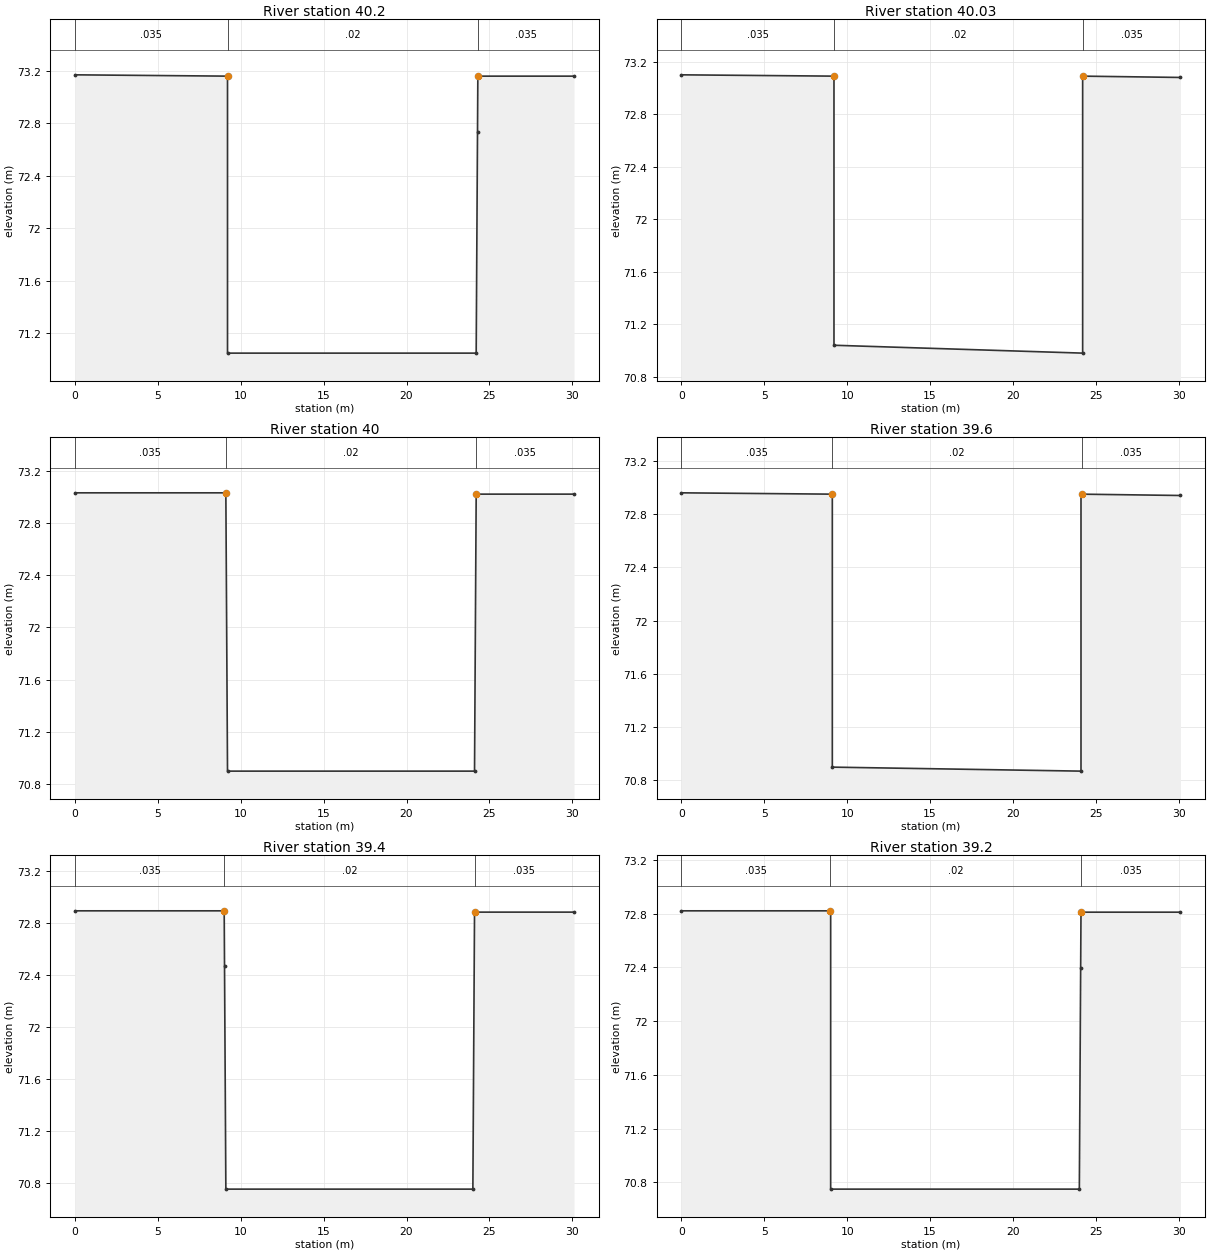
Type RM Length L Ch R = 1 ,40.2    ,0.2,0.2,0.2
XS GIS Cut Line= 2
1000002.86718118999990.7228087481000002.832190391000020.83751357
#Sta/Elev= 8
       0   73.17    9.1873.16003     9.2   73.16     9.2   71.05    24.2   71.05
   24.2872.73803    24.3   73.16    30.1   73.16
#Mann= 3 ,0,0
       0    .035       0     9.2     .02       0    24.3    .035       0
Bank Sta=9.2,24.3
XS Rating Curve= 0 ,0
Exp/Cntr=0.3,0.1

Type RM Length L Ch R = 1 ,40.03   ,0.2,0.2,0.2
XS GIS Cut Line= 2
1000002.66829607999990.7627571841000002.630398021000020.87851714
#Sta/Elev= 8
       0    73.1    9.1473.09007     9.2   73.09     9.2   71.04    24.2   70.98
    24.2   73.09   24.2473.08993    30.1   73.08
#Mann= 3 ,0,0
       0    .035       0     9.2     .02       0   24.24    .035       0
Bank Sta=9.2,24.24
XS Rating Curve= 0 ,0
Exp/Cntr=0.3,0.1

Type RM Length L Ch R = 1 ,40      ,0.2,0.2,0.2
XS GIS Cut Line= 2
1000002.46941097 999990.802705621000002.428605641000020.91952072
#Sta/Elev= 6
       0   73.03     9.1   73.03     9.2    70.9    24.1    70.9    24.2   73.02
    30.1   73.02
#Mann= 3 ,0,0
       0    .035       0     9.1     .02       0    24.2    .035       0
Bank Sta=9.1,24.2
XS Rating Curve= 0 ,0
Exp/Cntr=0.3,0.1

Type RM Length L Ch R = 1 ,39.6    ,0.2,0.2,0.2
XS GIS Cut Line= 2
1000002.27052587999990.8426540561000002.226813271000020.96052429
#Sta/Elev= 8
       0   72.96    9.0672.95004     9.1   72.95     9.1    70.9    24.1   70.87
    24.1   72.95   24.16 72.9499    30.1   72.94
#Mann= 3 ,0,0
       0    .035       0    9.06     .02       0   24.16    .035       0
Bank Sta=9.06,24.16
XS Rating Curve= 0 ,0
Exp/Cntr=0.3,0.1

Type RM Length L Ch R = 1 ,39.4    ,0.2,0.2,0.2
XS GIS Cut Line= 2
1000002.07164077999990.882602492 1000002.02502091000021.00152786
#Sta/Elev= 8
       0   72.89       9   72.89    9.0272.46199     9.1   70.75      24   70.75
    24.1   72.88   24.12   72.88    30.1   72.88
#Mann= 3 ,0,0
       0    .035       0       9     .02       0   24.12    .035       0
Bank Sta=9,24.12
XS Rating Curve= 0 ,0
Exp/Cntr=0.3,0.1

Type RM Length L Ch R = 1 ,39.2    ,0.2,0.2,0.2
XS GIS Cut Line= 2
1000001.87275567999990.9225509281000001.823228531000021.04253143
#Sta/Elev= 8
       0   72.82    8.98   72.82       9   72.82       9   70.75      24   70.75
   24.0872.39799    24.1   72.81    30.1   72.81
#Mann= 3 ,0,0
       0    .035       0    8.98     .02       0    24.1    .035       0
Bank Sta=8.98,24.1
XS Rating Curve= 0 ,0
Exp/Cntr=0.3,0.1

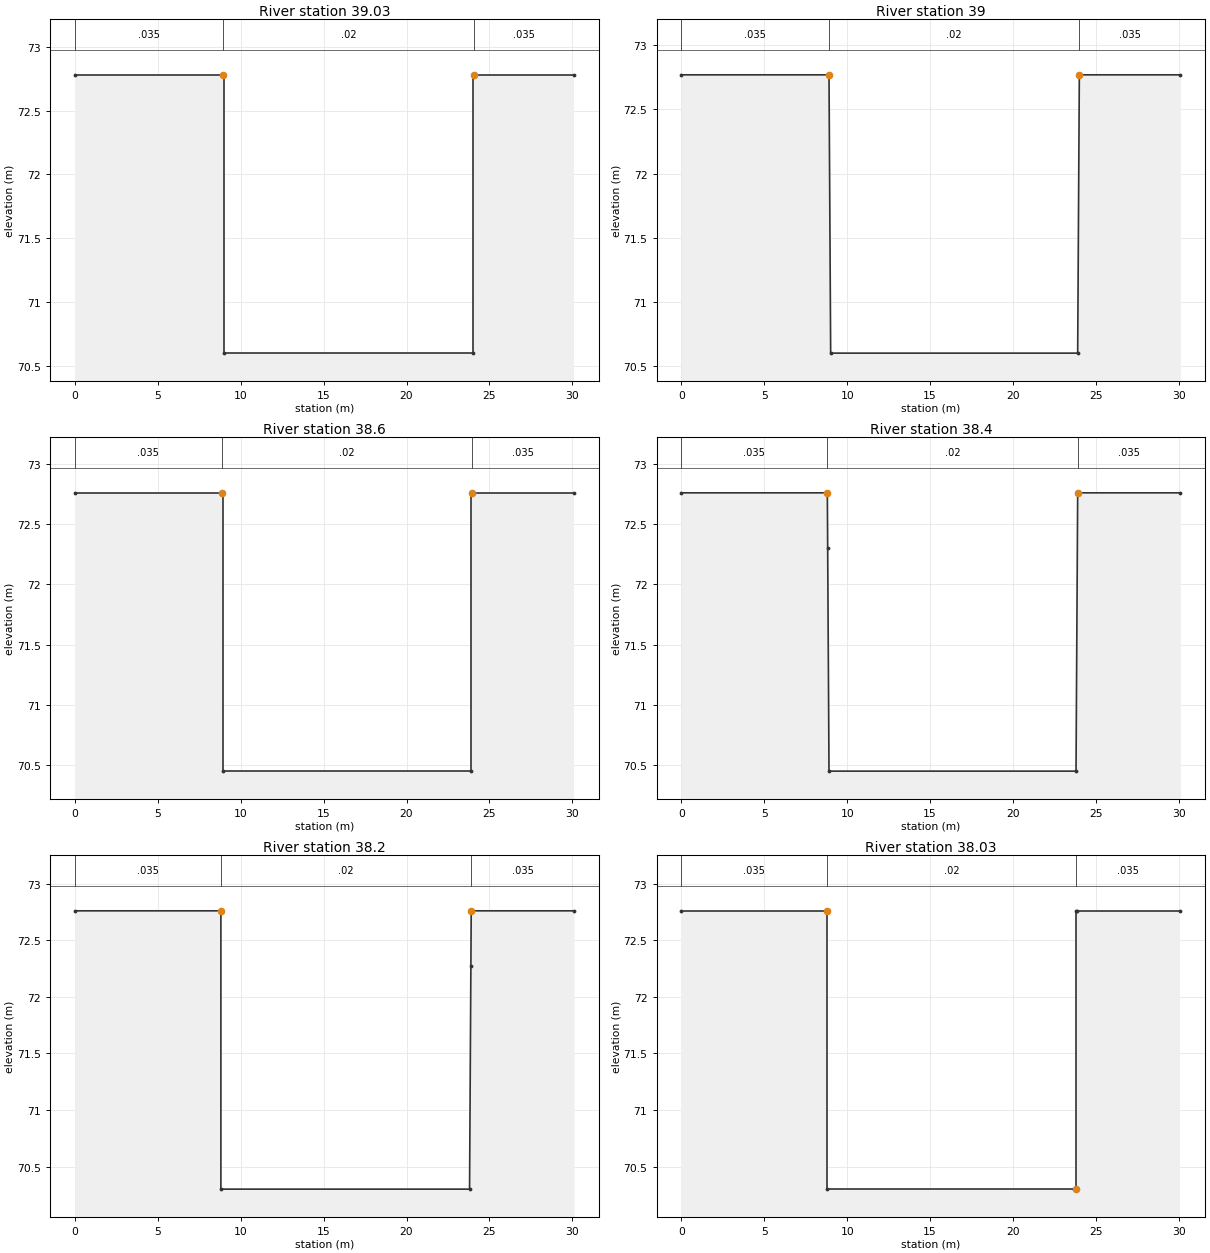
Type RM Length L Ch R = 1 ,39.03   ,0.2,0.2,0.2
XS GIS Cut Line= 2
1000001.67387056999990.9624993641000001.62143616  1000021.083535
#Sta/Elev= 8
       0   72.78    8.94   72.78       9   72.78       9    70.6      24    70.6
      24   72.78   24.04   72.78    30.1   72.78
#Mann= 3 ,0,0
       0    .035       0    8.94     .02       0   24.04    .035       0
Bank Sta=8.94,24.04
XS Rating Curve= 0 ,0
Exp/Cntr=0.3,0.1

Type RM Length L Ch R = 1 ,39      ,0.2,0.2,0.2
XS GIS Cut Line= 2
1000001.47498546  999991.00244781000001.419643781000021.12453857
#Sta/Elev= 6
       0   72.77     8.9   72.77       9    70.6    23.9    70.6      24   72.77
    30.1   72.77
#Mann= 3 ,0,0
       0    .035       0     8.9     .02       0      24    .035       0
Bank Sta=8.9,24
XS Rating Curve= 0 ,0
Exp/Cntr=0.3,0.1

Type RM Length L Ch R = 1 ,38.6    ,0.2,0.2,0.2
XS GIS Cut Line= 2
1000001.27610036999991.0423962361000001.217851411000021.16554215
#Sta/Elev= 8
       0   72.76    8.86   72.76     8.9   72.76     8.9   70.45    23.9   70.45
    23.9   72.76   23.96   72.76    30.1   72.76
#Mann= 3 ,0,0
       0    .035       0    8.86     .02       0   23.96    .035       0
Bank Sta=8.86,23.96
XS Rating Curve= 0 ,0
Exp/Cntr=0.3,0.1

Type RM Length L Ch R = 1 ,38.4    ,0.2,0.2,0.2
XS GIS Cut Line= 2
1000001.07721526999991.0823446711000001.016059041000021.20654572
#Sta/Elev= 8
       0   72.76     8.8   72.76    8.8272.29801     8.9   70.45    23.8   70.45
    23.9   72.76   23.92   72.76    30.1   72.76
#Mann= 3 ,0,0
       0    .035       0     8.8     .02       0   23.92    .035       0
Bank Sta=8.8,23.92
XS Rating Curve= 0 ,0
Exp/Cntr=0.3,0.1

Type RM Length L Ch R = 1 ,38.2    ,0.2,0.2,0.2
XS GIS Cut Line= 2
1000000.87833015999991.1222931071000000.814266671000021.24754929
#Sta/Elev= 8
       0   72.76    8.78   72.76     8.8   72.76     8.8    70.3    23.8    70.3
   23.8872.26799    23.9   72.76    30.1   72.76
#Mann= 3 ,0,0
       0    .035       0    8.78     .02       0    23.9    .035       0
Bank Sta=8.78,23.9
XS Rating Curve= 0 ,0
Exp/Cntr=0.3,0.1

Type RM Length L Ch R = 1 ,38.03   ,0.2,0.2,0.2
XS GIS Cut Line= 2
1000000.67944505999991.162241543 1000000.61247431000021.28855286
#Sta/Elev= 9
       0   72.76    8.74   72.76     8.8   72.76     8.8    70.3    23.7    70.3
    23.8    70.3    23.8   72.76   23.84   72.76    30.1   72.76
#Mann= 3 ,0,0
       0    .035       0     8.8     .02       0    23.8    .035       0
Bank Sta=8.8,23.8
XS Rating Curve= 0 ,0
Exp/Cntr=0.3,0.1

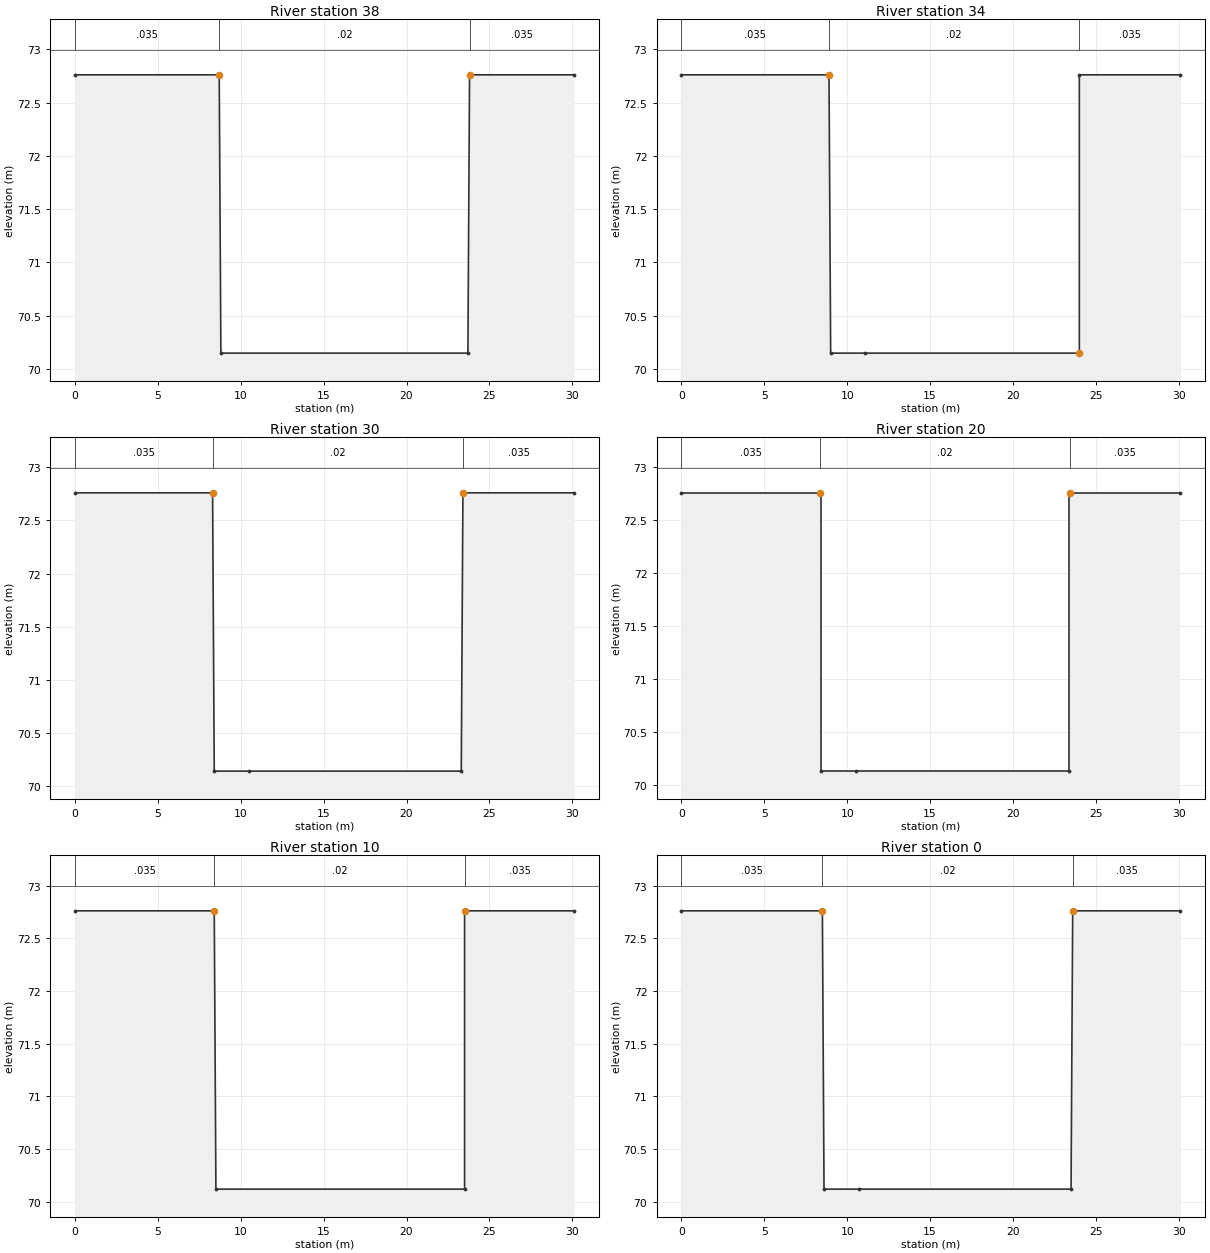
Type RM Length L Ch R = 1 ,38      ,0.45,0.45,0.45
XS GIS Cut Line= 2
1000000.48056066999991.2021898361000000.410682651000021.32955629
#Sta/Elev= 6
       0   72.76     8.7   72.76     8.8   70.15    23.7   70.15    23.8   72.76
    30.1   72.76
#Mann= 3 ,0,0
       0    .035       0     8.7     .02       0    23.8    .035       0
Bank Sta=8.7,23.8
XS Rating Curve= 0 ,0
Exp/Cntr(USF)=0,0
Exp/Cntr=0.3,0.1

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
Type RM Length L Ch R = 1 ,34      ,4.4,4.4,4.4
XS GIS Cut Line= 2
999996.893572629999990.974268492999996.7920384021000021.06224454
#Sta/Elev= 7
       0   72.76     8.9   72.76       9   70.15    11.1   70.15      24   70.15
      24   72.76    30.1   72.76
#Mann= 3 ,0,0
       0    .035       0     8.9     .02       0      24    .035       0
Bank Sta=8.9,24
XS Rating Curve= 0 ,0
Exp/Cntr=0.3,0.1

Type RM Length L Ch R = 1 ,30      ,9.9,9.9,9.9
XS GIS Cut Line= 2
999992.498602284999991.605186333999992.3970680571000021.69316238
#Sta/Elev= 7
       0   72.76     8.3   72.76     8.4   70.14    10.5   70.14    23.3   70.14
    23.4   72.76    30.1   72.76
#Mann= 3 ,0,0
       0    .035       0     8.3     .02       0    23.4    .035       0
Bank Sta=8.3,23.4
XS Rating Curve= 0 ,0
Exp/Cntr=0.3,0.1

Type RM Length L Ch R = 1 ,20      ,9.9,9.9,9.9
XS GIS Cut Line= 2
999982.594251518999991.539666923999982.4927172911000021.62764297
#Sta/Elev= 9
       0   72.76   8.375   72.76     8.4   72.76     8.4   70.13    10.5   70.13
    23.4   70.13    23.4   72.76   23.45   72.76    30.1   72.76
#Mann= 3 ,0,0
       0    .035       0   8.375     .02       0   23.45    .035       0
Bank Sta=8.375,23.45
XS Rating Curve= 0 ,0
Exp/Cntr=0.3,0.1

Type RM Length L Ch R = 1 ,10      ,1.98,1.98,1.98
XS GIS Cut Line= 2
999972.689900752999991.474147514999972.5883665251000021.56212356
#Sta/Elev= 7
       0   72.76     8.4   72.76     8.5   70.12    23.5   70.12    23.5   72.76
  23.525   72.76    30.1   72.76
#Mann= 3 ,0,0
       0    .035       0     8.4     .02       0  23.525    .035       0
Bank Sta=8.4,23.525
XS Rating Curve= 0 ,0
Exp/Cntr=0.3,0.1

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
Type RM Length L Ch R = 1 ,0       ,,,
XS GIS Cut Line= 2
999962.785557619999991.408628155999962.684023392 1000021.4966042
#Sta/Elev= 7
       0   72.76     8.5   72.76     8.6   70.12    10.7   70.12    23.5   70.12
    23.6   72.76    30.1   72.76
#Mann= 3 ,0,0
       0    .035       0     8.5     .02       0    23.6    .035       0
Bank Sta=8.5,23.6
XS Rating Curve= 0 ,0
Exp/Cntr(USF)=0,0
Exp/Cntr=0.3,0.1
LCMann Table=0

Chan Stop Cuts=-1
Use User Specified Reach Order=0
Composite Channel Slope=5